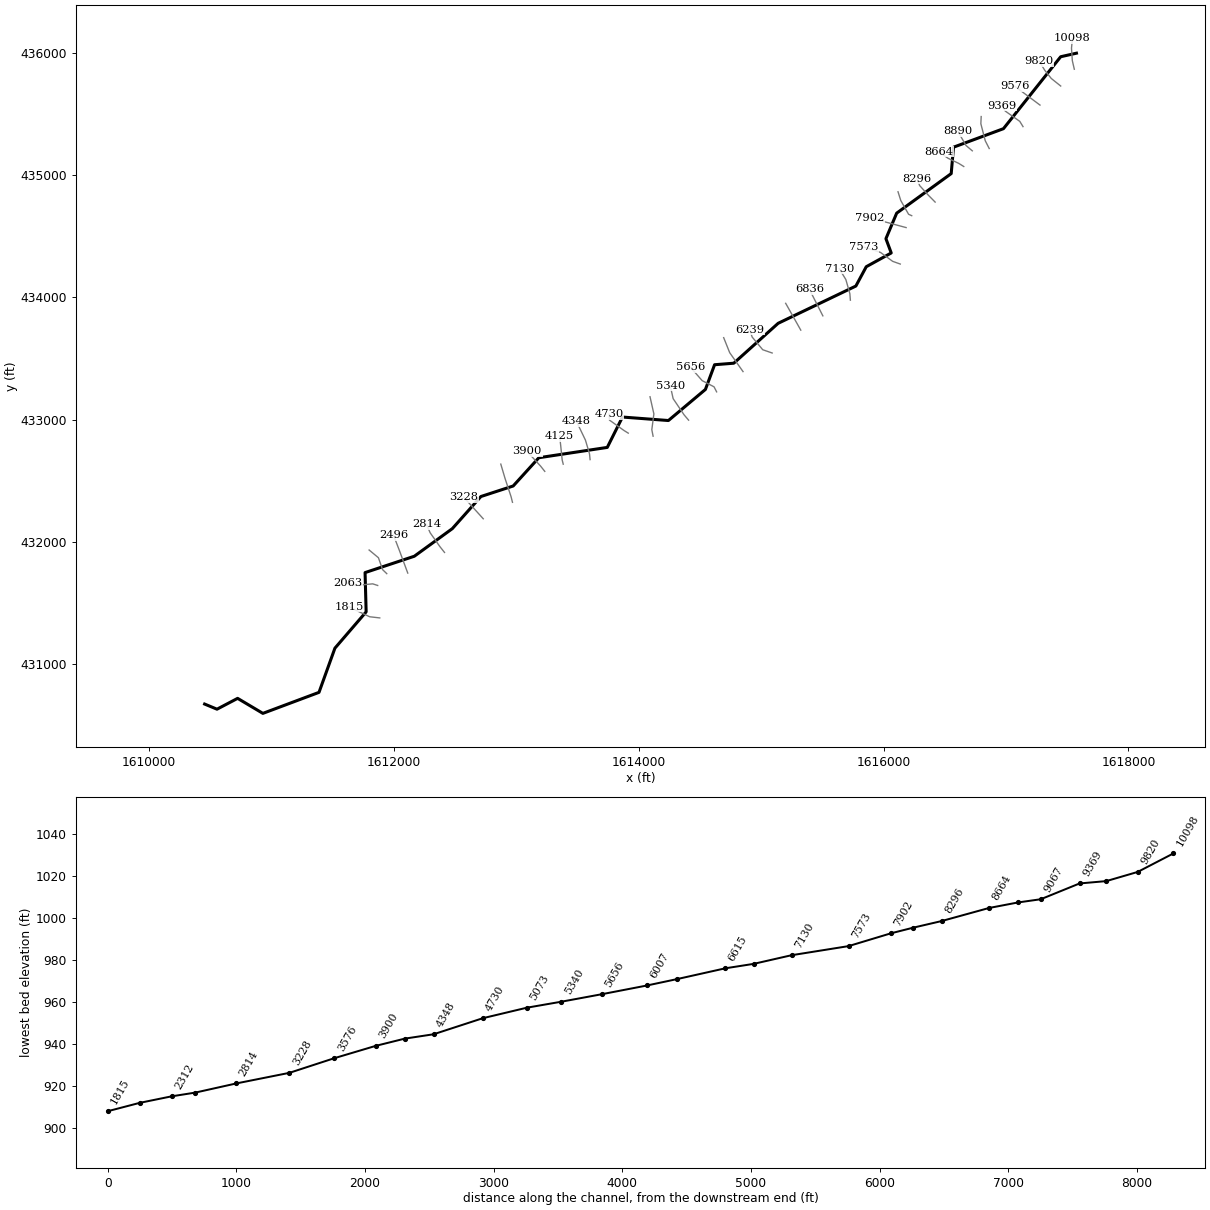
--- PROCTRCKT1.prj (project) ---

Proj Title=PROCTRCKT1
Current Plan=p01
Default Exp/Contr=0,0
English Units
Geom File=g01
Flow File=f01
Plan File=p01
BEGIN DESCRIPTION:
---------- MODELED AS PART OF WVEMD CTP PROGRAM, 2023----------
Stream Name: Proctor Creek Tributary 1
Flood Zone:  AFH
Wetzel County, WV
HEC-RAS Version: RAS 6.3
Vertical Datum: NAVD88
Projection: NAD 1983 StatePlane West Virginia S FIPS 4702 (US Feet)
Terrain: 1-meter West Virginia FEMA R3 South Central (collected 2018-2020)
Land Use: 2019 NLCD
Hydrologic Method:
WV SIR2010-5033 regression equations
Additional Model Notes:
None
END DESCRIPTION:
DSS Export Rating Curves= 0
DSS Export Rating Curve Sorted= 0
DSS Export Volume Flow Curves= 0
DXF OffsetX= 0
DXF OffsetY= 0
DXF ScaleX= 0
DXF ScaleY= 0

--- PROCTRCKT1.p01 (plan) ---

Plan Title=Floodplain
Program Version=6.30
Short Identifier=Floodplain
Geom File=g01
Flow File=f01
Subcritical Flow
K Sum by GR= 0
Std Step Tol= 0.01
Critical Tol= 0.01
Num of Std Step Trials= 20
Max Error Tol= 0.3
Flow Tol Ratio= 0.001
Split Flow NTrial= 30
Split Flow Tol= 0.02
Split Flow Ratio= 0.02
Log Output Level= 0
Friction Slope Method= 1
Unsteady Friction Slope Method= 2
Unsteady Bridges Friction Slope Method= 1
Parabolic Critical Depth
Global Vel Dist= 0 , 0 , 0
Global Log Level= 0
CheckData=True
Encroach Param=-1 ,0,0, 0
Mapping Interval=1HOUR
Computation Time Step Use Courant=        0
Computation Time Step Use Time Series=    0
Computation Time Step Count To Double=0
Computation Time Step Max Doubling=0
Computation Time Step Max Halving=0
Computation Time Step Residence Courant=0
Run HTab= 0
Run UNet= 0
Run Sediment= 0
Run PostProcess= 0
Run WQNet= 0
Run RASMapper= 0
UNET Theta= 0
UNET Theta Warmup= 0
UNET ZTol= 0
UNET ZSATol= 0
UNET MxIter= 0
UNET Max Iter WO Improvement= 0
UNET MaxInSteps= 0
UNET DtIC= 0
UNET DtMin= 0
UNET MaxCRTS= 0
UNET WFStab= 0
UNET SFStab= 0
UNET WFX= 1
UNET SFX= 1
UNET Gravity=32.17405
UNET 1D Methodology=Finite Difference
UNET DSS MLevel= 1
UNET Pardiso=0
UNET DZMax Abort= 0
UNET Use Existing IB Tables= 0
UNET Froude Reduction=False
UNET Froude Limit= 0
UNET Froude Power= 0
UNET D1 Cores= 0
UNET WindReference=Eulerian
UNET WindDragFormulation=Hsu (1988)
UNET D2 Coriolis=0
UNET D2 Cores= 0
UNET D2 Theta= 1
UNET D2 Theta Warmup= 1
UNET D2 Z Tol= 0.01
UNET D2 Volume Tol= 0.01
UNET D2 Max Iterations= 20
UNET D2 Equation= 0
UNET D2 RampUpFraction=0.1
UNET D2 TimeSlices= 1
UNET D2 Turbulence Formulation=Non-Conservative (original)
UNET D2 Eddy Viscosity=0.3
UNET D2 Transverse Eddy Viscosity=0.1
UNET D2 Smagorinsky Mixing=0
UNET D2 BCVolumeCheck=0
UNET D2 Cores=0
UNET D2 SolverType=PARDISO (Direct)
UNET D2 Minimum Iterations= 3
UNET D2 Maximum Iterations= 30
UNET D2 Restart Number= 10
UNET D2 Relaxation Coeff=1.3
UNET D2 SOR Precondition Iterations= 10
UNET D2 ILUT Maximum Fill= 8
UNET D2 ILUT Tolerance=1E-08
UNET D2 Convergence Tolerance=0.00001
UNET D1D2 MaxIter= 0
UNET D1D2 ZTol=0.01
UNET D1D2 QTol=0.1
UNET D1D2 MinQTol=1
Write IC File= 0
Write IC File at Fixed DateTime=0
Write IC File at Sim End=0
Echo Input=False
Echo Parameters=False
Echo Output=False
Write Detailed= 0
HDF Write Warmup=0
HDF Write Time Slices=0
HDF Flush=0
HDF Compression= 1
HDF Chunk Size= 1
HDF Spatial Parts= 1
HDF Use Max Rows=0
HDF Fixed Rows= 1
Calibration Method= 0
Calibration Iterations= 20
Calibration Max Change=0.05
Calibration Tolerance=0.2
Calibration Maximum=1.5
Calibration Minimum=0.5
Calibration Optimization Method= 1
WQ AD Non Conservative
WQ ULTIMATE=-1
WQ Max Comp Step=1HOUR
WQ Output Interval=15MIN
WQ Output Selected Increments= 0
WQ Output face flow=0
WQ Output face velocity=0
WQ Output face area=0
WQ Output face dispersion=0
WQ Output cell volume=0
WQ Output cell surface area=0
WQ Output cell continuity=0
WQ Output cumulative cell continuity=0
WQ Output face conc=0
WQ Output face dconc_dx=0
WQ Output face courant=0
WQ Output face peclet=0
WQ Output face adv mass=0
WQ Output face disp mass=0
WQ Output cell mass=0
WQ Output cell source sink temp=0
WQ Output nsm pathways=0
WQ Output nsm derived pathways=0
WQ Create Restart=0
WQ Fixed Restart=0
WQ System Summary=0
WQ Write To DSS=0
Sorting and Armoring Iterations= 10
XS Update Threshold= 0.02
Bed Roughness Predictor= 0
Hydraulics Update Threshold= 0.02
Energy Slope Method= 1
Volume Change Method= 1
Sediment Retention Method= 0
Sediment TS Multiplier= 1
Warm Up Method= 0
XS Weighting Method= 0
Number of US Weighted Cross Sections= 1
Number of DS Weighted Cross Sections= 1
Upstream XS Weight=0
Main XS Weight=1
Downstream XS Weight=0
Number of DS XS's Weighted with US Boundary= 1
Upstream Boundary Weight= 1
Weight of XSs Associated with US Boundary= 0
Number of US XS's Weighted with DS Boundary= 1
Downstream Boundary Weight= 0.5
Weight of XSs Associated with DS Boundary= 0.5
Percentile Method= 0
Sediment Output Level= 3
Mass or Volume Output= 0
Output Increment Type= 1
Profile and TS Output Increment= 1
Transport Output Increment 1
XS Output Flag= 0
XS Output Increment= 10
Read HDF5 Sediment Hotstart= 0
Sediment Hotstart Type= 0
Write Gradation File= 0
Read Gradation Hotstart= 0
Write HDF5 File= 1
Write Binary Output= 1
Write DSS Sediment File= 0
DSS Sediment Output Type= 1
SV Curve= 0
Specific Gage Flag= 0
Subcell Erosion Methods= 0
Subcell Deposition Methods= 0
Advection Scheme= 1
Matrix Solver= 0
Implicit Weighting Factor= 1
Maximum Outer Loop Convergence Iterations= 5
Convergence Maximum Absolute= 0.001
Convergence RMSE= 0.0001
Grain Fractions Max Abs Error= 0.001
Max Subgrid Regions= 1
Max Subgrid Length Scale= 3.402823E+38
Initial Layer Thickness= 3.402823E+38
Min Layer Thickness= 3.402823E+38
Max Layer Thickness= 3.402823E+38
Number of Layers= 5

--- PROCTRCKT1.f01 (steady flow) ---

Flow Title=Flow
Program Version=6.30
Number of Profiles= 1
Profile Names=F01pct
River Rch & RM=PROCTRCKT1,Main,10098
     648
River Rch & RM=PROCTRCKT1,Main,8296
     730
River Rch & RM=PROCTRCKT1,Main,7130
     867
River Rch & RM=PROCTRCKT1,Main,4348
    1080
Boundary for River Rch & Prof#=PROCTRCKT1,Main            , 1
Up Type= 0
Dn Type= 3
Dn Slope=0.01742
DSS Import GetInterval= 0
DSS Import GetPeak= 0
DSS Import FillOption= 0

--- PROCTRCKT1.g01 (geometry) ---

Geom Title=Geometry
Program Version=6.30

River Reach=PROCTRCKT1      ,Main
Reach XY= 30
     1617575.474      435995.792     1617446.575      435966.686
     1616979.096      435378.624     1616571.017      435227.154
1616552.23080803   435011.3136131616106.81742939434688.086309613
1616018.84639159434479.205306603     1616062.255      434362.548
     1615858.216      434250.022     1615773.274      434092.018
     1615138.286      433787.295     1614775.946      433461.188
     1614619.129      433448.714     1614544.285      433246.754
     1614241.938      432992.521      1613866.53      433021.033
     1613742.383      432772.741     1613183.428      432688.392
     1612973.746      432457.326     1612710.009      432371.196
     1612476.567      432108.647     1612165.904      431882.927
     1611763.765      431749.276     1611772.485      431428.207
     1611517.397      431131.301     1611387.382      430770.148
     1610928.908      430598.316     1610722.481      430721.108
     1610554.069       430632.53     1610452.958      430674.516

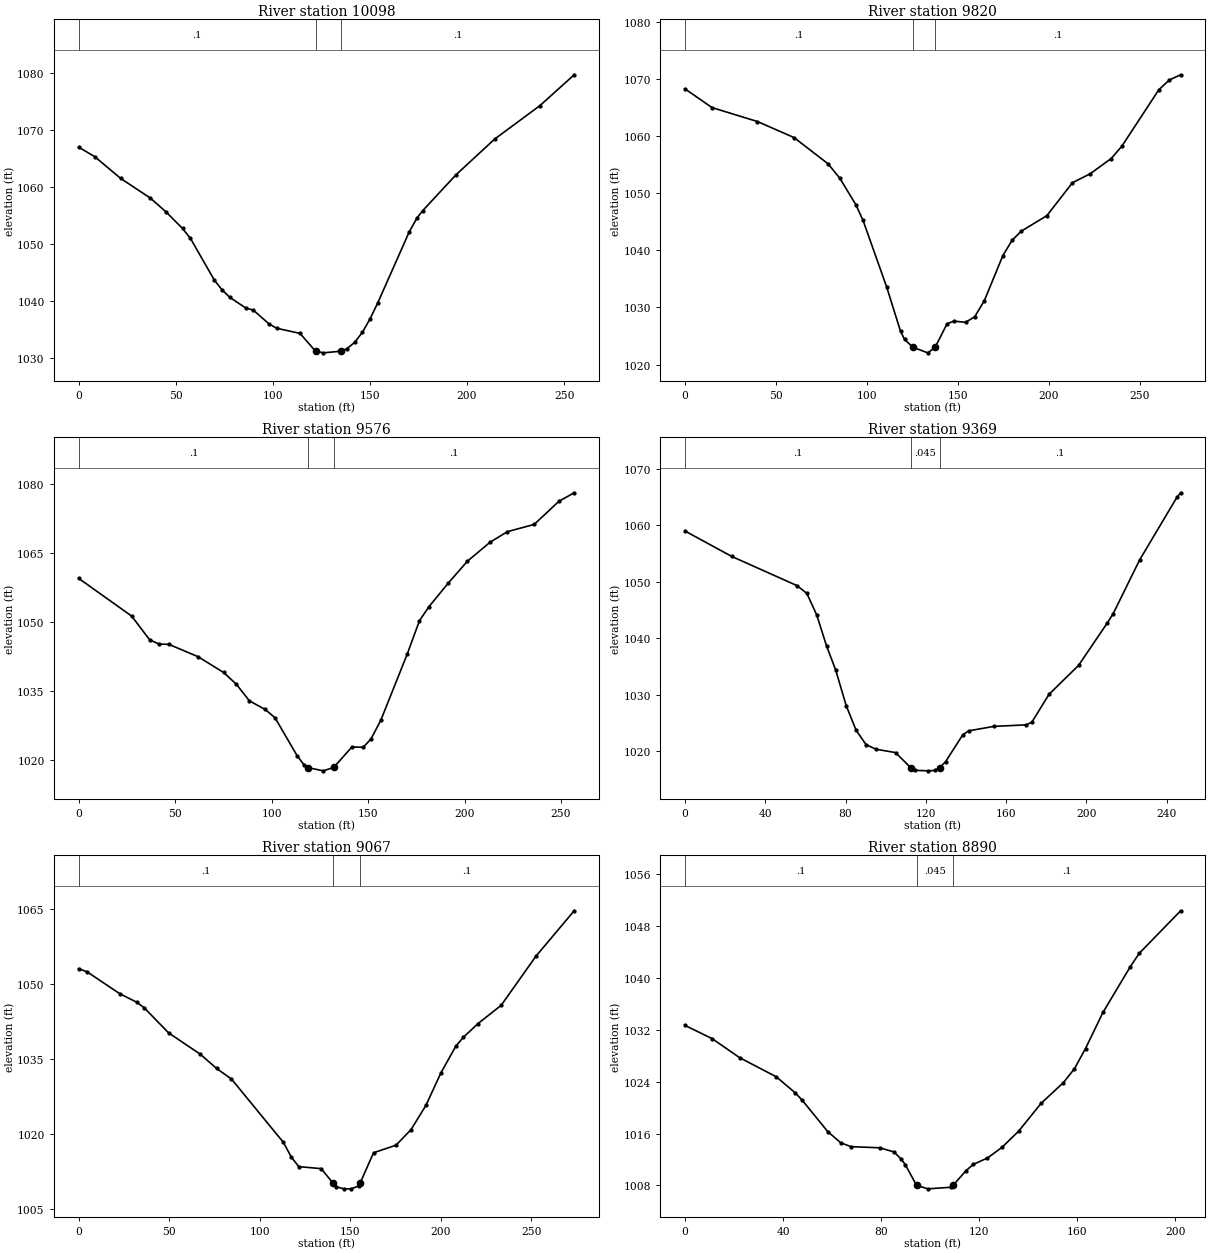
Type RM Length L Ch R = 1 ,10098   ,271.4,277.9,279.7
XS GIS Cut Line= 4
1617557.98541615435864.4588665521617541.76272586435934.472582546
1617534.93211942436036.9316791221617542.61655167436117.191304773
#Sta/Elev= 30
       0 1066.98     8.3 1065.31    21.6 1061.51      37 1058.03      45 1055.63
    53.5 1052.72    57.6 1050.97    69.9 1043.66    73.9 1041.94    77.9 1040.62
      86 1038.79      90 1038.39      98    1036     102 1035.22     114 1034.32
     122  1031.2   126.1 1030.91  135.05  1031.2   138.1 1031.62   142.1 1032.73
   146.1 1034.49   150.1 1036.88   154.1 1039.71   170.2 1052.08   174.2 1054.54
   177.2 1055.84   194.3 1062.12   214.3 1068.41   237.6 1074.27   255.2 1079.67
#Mann= 3 ,-1,0
       0      .1       0     122    .045       0  135.05      .1       0
Bank Sta=122,135.05
XS Rating Curve= 0 ,0
Exp/Cntr(USF)=0,0
Exp/Cntr=0.3,0.1

Type RM Length L Ch R = 1 ,9820    ,242.2,244.1,245.5
XS GIS Cut Line= 4
1617446.82526072435727.2915753271617369.98093829 435788.95677234
1617316.85399933435855.3654460471617270.36792773 435931.26107314
#Sta/Elev= 30
       0 1068.23    14.8 1064.97    39.8 1062.53    59.9 1059.73    78.7 1055.12
    85.1 1052.61    93.9    1048    97.9 1045.22   110.9 1033.57   118.5 1025.83
   120.7 1024.45   125.2 1023.05   133.5 1022.06   137.51023.008   144.1 1027.14
   147.9 1027.61   154.3  1027.4   159.3 1028.37   164.6 1031.18   174.8 1039.07
   179.9 1041.76   184.9 1043.34     199 1046.06   213.1 1051.83   222.8 1053.38
   234.4 1056.06   240.2 1058.19   260.6 1068.09   266.4 1069.81   272.6 1070.71
#Mann= 3 ,-1,0
       0      .1       0   125.2    .045       0   137.5      .1       0
Bank Sta=125.2,137.5
XS Rating Curve= 0 ,0
Exp/Cntr(USF)=0,0
Exp/Cntr=0.3,0.1

Type RM Length L Ch R = 1 ,9576    ,207.4,207.6,207.7
XS GIS Cut Line= 2
 1617277.5931949435571.5760683931617071.82117595435725.264713257
#Sta/Elev= 30
       0 1059.51    27.5  1051.3    36.8 1046.15    41.7 1045.23    46.8 1045.16
    61.8  1042.5    75.1 1039.06    81.7 1036.52    88.5 1032.89    96.7 1031.01
   101.8  1029.2   113.2 1020.98   116.7 1019.04   118.9 1018.38   126.7 1017.68
   132.2 1018.42   141.6 1022.86   147.5  1022.8   151.6 1024.66   156.6 1028.68
   170.4 1043.17   176.6 1050.28   181.6 1053.38   191.6  1058.5   201.5 1063.24
   213.2 1067.35   222.2 1069.65   236.1 1071.23   248.9 1076.25   256.8  1078.1
#Mann= 3 ,-1,0
       0      .1       0   118.9    .045       0   132.2      .1       0
Bank Sta=118.9,132.2
XS Rating Curve= 0 ,0
Exp/Cntr(USF)=0,0
Exp/Cntr=0.3,0.1

Type RM Length L Ch R = 1 ,9369    ,307,301.7,296.8
XS GIS Cut Line= 4
1617138.90618039435395.3189461541617112.62542212435438.198078071
1616993.67041099435522.5731441021616967.38965272 435566.14387492
#Sta/Elev= 30
       0 1059.01    23.3 1054.51    55.8 1049.35    60.7 1047.97    65.6 1044.17
    70.5 1038.68    75.1 1034.36    80.3 1028.11    85.2 1023.77    90.2  1021.2
    95.1 1020.39   104.9 1019.79   112.41017.138   114.7 1016.65   121.2 1016.56
   124.5 1016.63   126.9 1017.15   129.8 1018.16   138.4 1022.93   141.3 1023.64
   153.9 1024.43     170  1024.7   172.8 1025.16   181.4 1030.11   196.1 1035.22
   210.4 1042.72   213.3 1044.33   226.5 1053.86   245.1 1064.97     247 1065.79
#Mann= 3 ,-1,0
       0      .1       0   112.4    .045       0   126.9      .1       0
Bank Sta=112.4,126.9
XS Rating Curve= 0 ,0
Exp/Cntr(USF)=0,0
Exp/Cntr=0.3,0.1

Type RM Length L Ch R = 1 ,9067    ,175.9,177.4,179.8
XS GIS Cut Line= 4
1616862.82266051435216.3748250091616830.37727993435279.557934564
1616794.51659613435418.7315407471616797.07807354435477.645521278
#Sta/Elev= 30
       0    1053     4.7 1052.36    22.7    1048    32.2 1046.27    36.2 1045.19
    49.7 1040.17    67.2 1035.91    76.2 1033.06    84.4 1030.96   113.1  1018.3
   117.5 1015.35   121.6 1013.46     134 1013.05   140.6 1010.11   142.3 1009.45
   146.4 1009.02   150.5 1009.02   154.7 1009.59   155.41010.112   162.9 1016.23
   175.3 1017.74   183.6 1020.85   191.8 1025.68   200.1 1032.18   208.3  1037.5
   212.5 1039.29   220.6 1042.03   233.4 1045.68   252.5 1055.45   273.7 1064.56
#Mann= 3 ,-1,0
       0      .1       0   140.6    .045       0   155.4      .1       0
Bank Sta=140.6,155.4
XS Rating Curve= 0 ,0
Exp/Cntr(USF)=0,0
Exp/Cntr=0.3,0.1

Type RM Length L Ch R = 1 ,8890    ,218.5,225.4,227.7
XS GIS Cut Line= 4
1616724.46786039435197.5019822691616672.98216436435241.303246055
1616632.25467348435312.000022693 1616607.6644903435358.875059376
#Sta/Elev= 30
       0 1032.68      11 1030.65    22.3  1027.7    37.2 1024.76      45 1022.26
    47.7 1021.18    58.2  1016.3    63.5 1014.58    67.6 1013.99    79.4 1013.81
    85.2 1013.17    88.2 1012.04    89.8 1011.21    94.4 1008.02      99 1007.48
   108.3 1007.72   109.4 1008.06   114.5 1010.26   117.5 1011.25   123.3 1012.23
   129.2 1013.87     136 1016.36   145.2 1020.67   154.3 1023.87   158.8 1026.01
   163.3 1029.12   170.4 1034.68   181.4 1041.64   185.2  1043.8   202.1 1050.37
#Mann= 3 ,-1,0
       0      .1       0    94.4    .045       0   109.4      .1       0
Bank Sta=94.4,109.4
XS Rating Curve= 0 ,0
Exp/Cntr(USF)=0,0
Exp/Cntr=0.3,0.1

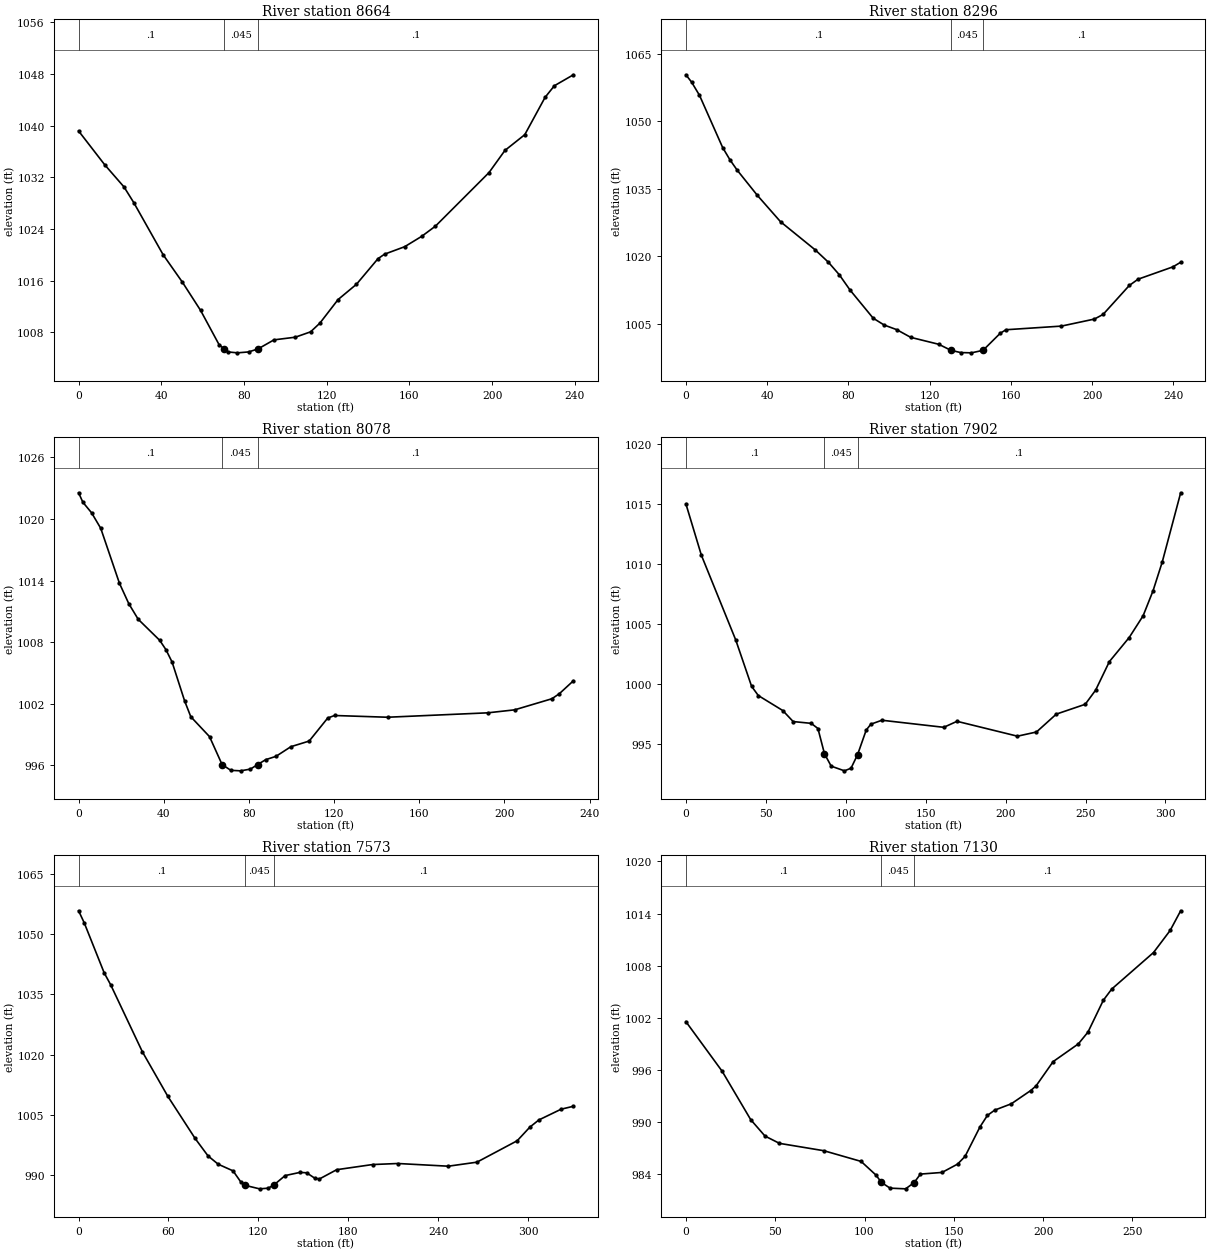
Type RM Length L Ch R = 1 ,8664    ,370.6,368.3,364.2
XS GIS Cut Line= 4
1616654.80621578435069.3364043331616614.07872489435094.695030735
1616527.24464054435136.1909648491616448.86343166435189.981990551
#Sta/Elev= 30
       0 1039.18    12.6 1033.96      22  1030.5    26.7 1028.08    40.9 1020.01
    50.2 1015.77      59  1011.4    67.9 1006.12   70.27 1005.46    72.3 1004.97
    76.8 1004.83    82.2 1004.97    86.8 1005.44    94.5 1006.84   104.8 1007.25
   112.2 1008.08   116.7 1009.43   125.5 1013.08   134.4 1015.45   144.8 1019.41
     148 1020.11   157.7 1021.26     166 1022.88   172.6 1024.45   198.5 1032.74
   206.2 1036.17   215.8 1038.61   225.6 1044.38   230.1 1046.18   239.3 1047.88
#Mann= 3 ,-1,0
       0      .1       0   70.27    .045       0    86.8      .1       0
Bank Sta=70.27,86.8
XS Rating Curve= 0 ,0
Exp/Cntr(USF)=0,0
Exp/Cntr=0.3,0.1

Type RM Length L Ch R = 1 ,8296    ,220.2,218.2,216.5
XS GIS Cut Line= 4
1616420.85150351434778.5243893241616363.64517459 434836.58454405
 1616294.4852844434913.4288664821616273.13963928 434968.07371799
#Sta/Elev= 30
       0 1060.35     2.8 1058.73     6.7 1055.79    18.1 1044.19    21.7 1041.46
    25.3 1039.14    35.2 1033.56    46.6 1027.71    63.7 1021.45    70.2  1018.7
    75.5 1015.95    80.8 1012.55    92.2 1006.29    97.6 1004.77   103.8 1003.74
   110.7 1002.03   124.5 1000.49  130.49  999.15   135.3  998.65   140.6  998.59
   146.3  999.15   154.8 1002.95   157.6 1003.72   184.9 1004.53   201.1 1006.09
   205.4 1007.12   218.3 1013.55   222.6 1014.94   239.8 1017.69   243.6 1018.71
#Mann= 3 ,-1,0
       0      .1       0  130.49    .045       0   146.3      .1       0
Bank Sta=130.49,146.3
XS Rating Curve= 0 ,0
Exp/Cntr(USF)=0,0
Exp/Cntr=0.3,0.1

Type RM Length L Ch R = 1 ,8078    ,166.4,176,181.2
XS GIS Cut Line= 4
1616229.64376528434667.3767627871616204.02899113434678.761106851
1616140.46640344434790.7071568141616117.69771532434862.808002553
#Sta/Elev= 30
       0 1022.55       2 1021.63     6.1  1020.6    10.4 1019.09    19.2 1013.73
    23.6 1011.74      28 1010.23    38.1 1008.18      41 1007.28    43.9 1006.07
    49.8 1002.28    52.7 1000.74    61.5   998.8    67.4  996.08    71.5  995.52
    76.1  995.47    80.7  995.64   84.07  996.08    87.9  996.56    92.7  996.88
    99.7  997.82   108.3  998.37     117 1000.61   120.2 1000.86   145.1 1000.69
   192.2 1001.12   204.8 1001.41   222.3 1002.49   225.8 1002.98   232.4 1004.24
#Mann= 3 ,-1,0
       0      .1       0    67.4    .045       0   84.07      .1       0
Bank Sta=67.4,84.07
XS Rating Curve= 0 ,0
Exp/Cntr(USF)=0,0
Exp/Cntr=0.3,0.1

Type RM Length L Ch R = 1 ,7902    ,327.4,328.7,320.2
XS GIS Cut Line= 2
1616183.83695955434570.000775836 1615885.0556341434650.667851674
#Sta/Elev= 30
       0    1015     9.7 1010.71    31.2 1003.64    41.1  999.78    45.3  999.01
    60.6  997.76    67.1  996.84    78.4  996.69    82.6  996.26    86.7  994.15
    90.9  993.12    99.2  992.73   103.3  992.95   107.4  994.08   112.8  996.13
   115.7  996.62   122.6  996.95   161.3  996.36   169.6  996.86   207.4  995.62
   219.3  995.97   231.7  997.46   249.8  998.28   256.3  999.46   264.9 1001.84
   277.3 1003.85     286 1005.66   292.2 1007.74     298 1010.16   309.5 1015.92
#Mann= 3 ,-1,0
       0      .1       0    86.7    .045       0   107.4      .1       0
Bank Sta=86.7,107.4
XS Rating Curve= 0 ,0
Exp/Cntr(USF)=0,0
Exp/Cntr=0.3,0.1

Type RM Length L Ch R = 1 ,7573    ,446.4,443.1,433
XS GIS Cut Line= 5
1616136.25124464434271.8345799721616074.00734347434293.965744832
 1615975.1087005434366.5836295311615924.62198067434383.873602078
1615840.24691464434409.462761448
#Sta/Elev= 30
       0 1055.77     3.8 1052.74    17.1 1040.32    21.4 1037.38    42.6 1020.69
    59.6 1009.61    77.8  999.15    86.4  994.82    93.2  992.75   103.1   991.1
   108.1  988.44     111  987.51   120.8  986.63   126.5  986.79   130.3987.5768
   137.9  989.93   147.8  990.72   152.2  990.62   157.7  989.27   160.8  989.09
   172.3  991.39   196.2  992.67   213.1  992.93   246.8  992.26   265.9  993.26
   292.8  998.59   301.2 1001.96   307.2 1003.75   322.1 1006.43   330.3 1007.16
#Mann= 3 ,-1,0
       0      .1       0     111    .045       0   130.3      .1       0
Bank Sta=111,130.3
XS Rating Curve= 0 ,0
Exp/Cntr(USF)=0,0
Exp/Cntr=0.3,0.1

Type RM Length L Ch R = 1 ,7130    ,292.6,294.4,295.6
XS GIS Cut Line= 4
1615728.46434638433976.3235556341615724.24792265434030.082958159
1615691.57063877434144.9805047311615637.81123624434233.525403006
#Sta/Elev= 30
       0 1001.55    20.3  995.83    36.3  990.25    44.3  988.36    52.4  987.52
    77.3  986.67    98.1  985.44   106.4  983.87   109.5983.0156   114.3  982.36
     123  982.28   127.8983.0009   131.3  983.98   143.4  984.17   152.1  985.13
   156.3  986.02   164.6   989.4   168.8  990.74   172.9  991.35   182.2  992.08
     193   993.6     196  994.13   205.6  996.94   219.7  998.98   225.1 1000.34
   233.7 1004.01   238.4  1005.3   261.8 1009.51   271.1 1012.05     277 1014.32
#Mann= 3 ,-1,0
       0      .1       0   109.5    .045       0   127.8      .1       0
Bank Sta=109.5,127.8
XS Rating Curve= 0 ,0
Exp/Cntr(USF)=0,0
Exp/Cntr=0.3,0.1

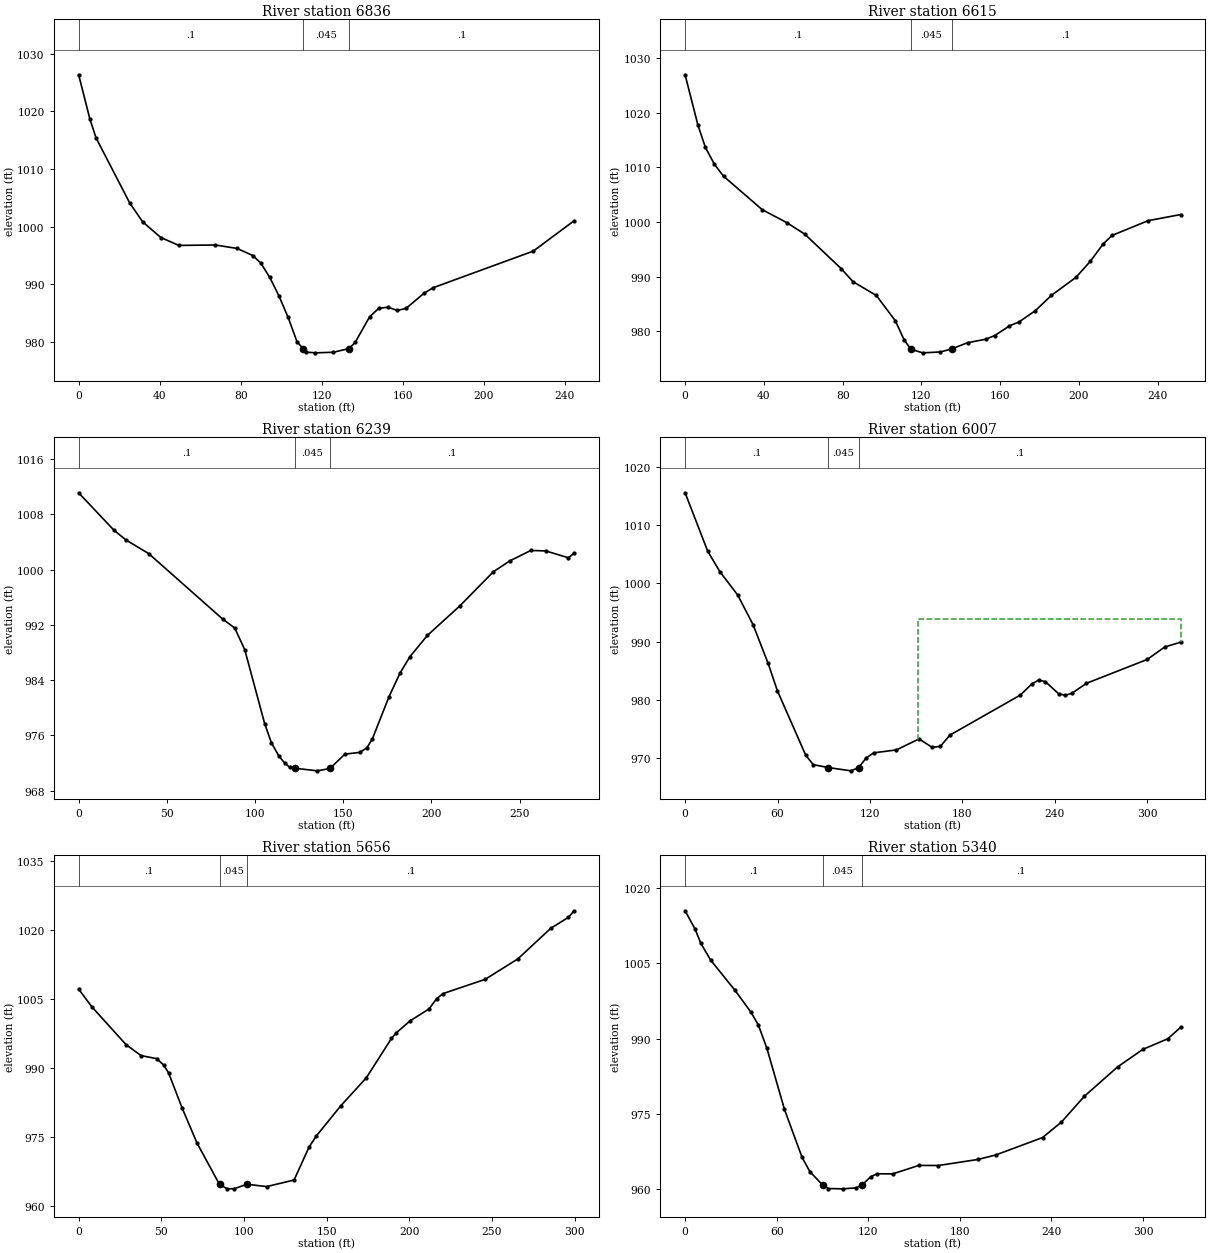
Type RM Length L Ch R = 1 ,6836    ,219.9,220.3,221
XS GIS Cut Line= 2
1615503.53089712433848.3631928921615392.84977427434066.563120785
#Sta/Elev= 30
       0 1026.34     5.6 1018.62     8.6  1015.4    25.2 1004.14    31.6 1000.86
    40.6  998.13    49.5  996.77    67.5  996.84    78.3  996.24      86  995.01
    89.9  993.73    94.4  991.22    98.9  988.03   103.4  984.34   107.8  980.11
     111  978.79   112.3  978.28   116.8  978.15   125.8  978.25   133.6   978.9
   136.6  979.99   143.7   984.4   148.2  985.86   152.7  986.06   157.4  985.49
   161.7  985.86   170.6  988.49   175.1  989.44   224.5  995.78   244.7 1001.05
#Mann= 3 ,-1,0
       0      .1       0     111    .045       0   133.6      .1       0
Bank Sta=111,133.6
XS Rating Curve= 0 ,0
Exp/Cntr(USF)=0,0
Exp/Cntr=0.3,0.1

Type RM Length L Ch R = 1 ,6615    ,374.6,376.3,378.2
XS GIS Cut Line= 2
1615323.32242806433731.5413340511615199.99203404433950.795367877
#Sta/Elev= 30
       0 1026.92     6.5 1017.72    10.3 1013.63    14.9 1010.53    19.5 1008.36
    39.2 1002.22    51.6  999.87    60.8  997.74    79.2  991.46    85.3  989.04
    97.1  986.53   106.7  981.92   111.3  978.34   114.7  976.68   120.6  976.03
   129.6  976.19   135.3  976.74   143.4  977.88   152.6  978.52   157.2  979.19
   164.6  980.94   169.7  981.72   177.9  983.77     186  986.55   198.5  989.86
   205.8  992.81   212.3  995.97   216.8  997.52   235.1 1000.22   251.6 1001.34
#Mann= 3 ,-1,0
       0      .1       0   114.7    .045       0   135.3      .1       0
Bank Sta=114.7,135.3
XS Rating Curve= 0 ,0
Exp/Cntr(USF)=0,0
Exp/Cntr=0.3,0.1

Type RM Length L Ch R = 1 ,6239    ,233,232.2,231.4
XS GIS Cut Line= 4
1615089.66463254433544.5618289161615012.48219509433571.326706419
1614926.53343791433674.474571297  1614904.410227433735.638742651
#Sta/Elev= 30
       0 1011.12    20.1 1005.68      27 1004.26    39.7 1002.32    81.7  992.83
    88.5  991.54    94.2   988.4   105.5  977.69   109.3  974.93   113.5  973.02
   116.9  971.97   119.7  971.38   122.6  971.24   135.3  970.86   142.5   971.2
     151  973.28   159.5  973.53   163.5  974.21   166.6  975.51     176  981.59
   182.2  984.99   187.9   987.4   197.8  990.48     216   994.7   235.2  999.69
   244.4 1001.24   256.4 1002.77   264.9  1002.7   277.7 1001.71     281 1002.38
#Mann= 3 ,-1,0
       0      .1       0   122.6    .045       0   142.5      .1       0
Bank Sta=122.6,142.5
XS Rating Curve= 0 ,0
Exp/Cntr(USF)=0,0
Exp/Cntr=0.3,0.1

Type RM Length L Ch R = 1 ,6007    ,346.4,351,354
XS GIS Cut Line= 3
1614851.56638679433392.4875180051614742.64210716433547.089721344
1614693.45049701433670.068746727
#Sta/Elev= 30
       0 1015.57    14.7 1005.52    22.6 1002.01    34.1  998.03    44.1  992.93
    53.9  986.27    59.9  981.58    78.3   970.5    83.2  968.89      93  968.39
   107.7  967.83   112.6  968.39   117.5  970.03   122.4  970.92   137.1  971.42
   151.8  973.31   160.4  971.85   165.7  972.05   171.9  973.97   217.5  980.83
   225.1  982.76   229.5  983.42   233.8  983.14   242.4  981.07   246.7   980.8
     251  981.14   260.5  982.86   299.9  986.95   311.3   989.1   321.6  989.91
#Mann= 3 ,-1,0
       0      .1       0      93    .045       0   112.6      .1       0
#XS Ineff= 2 , 0
                          150.97          993.91
Permanent Ineff=
       F       F
Bank Sta=93,112.6
XS Rating Curve= 0 ,0
Exp/Cntr(USF)=0,0
Exp/Cntr=0.3,0.1

Type RM Length L Ch R = 1 ,5656    ,319.7,315.5,310.1
XS GIS Cut Line= 4
1614635.75374133433226.9691086711614614.67162269433268.079240013
1614517.69387696433318.6763247421614422.85374431433427.202447265
#Sta/Elev= 30
       0 1007.19       8 1003.33    28.7  995.08    37.7  992.71    47.2  992.03
    51.4  990.66    54.4  988.93    62.6  981.27    71.6  973.64    85.2  964.62
    89.9  963.66    94.2   963.7   101.8  964.66   113.7  964.15   130.3  965.58
   139.3  972.72   143.8   975.2   158.5  981.74     174  987.86   189.2  996.43
     192  997.62   200.5 1000.28   211.9 1002.86   216.5 1005.09   220.4 1006.21
   245.9 1009.32   265.7 1013.79   285.5 1020.43   296.2 1022.83   299.7 1024.26
#Mann= 3 ,-1,0
       0      .1       0    85.2    .045       0   101.8      .1       0
Bank Sta=85.2,101.8
XS Rating Curve= 0 ,0
Exp/Cntr(USF)=0,0
Exp/Cntr=0.3,0.1

Type RM Length L Ch R = 1 ,5340    ,276.2,267.1,257.7
XS GIS Cut Line= 4
1614406.79432207432995.6189006591614370.35609232433038.563957142
1614280.56188331433171.3032226351614257.13730705 433276.71381582
#Sta/Elev= 30
       0  1015.5     6.5 1011.87    10.3 1009.02    16.7 1005.68    32.7  999.64
    43.2  995.26      48  992.72    53.6  988.06    65.1   975.9    76.6  966.36
    81.7  963.51   90.03960.8526    93.9  960.13   103.2  960.07   111.8  960.26
  115.82960.8209   121.5  962.46   125.6  963.07     136  963.05   153.1  964.74
   165.9  964.72   191.9  965.93   203.6  966.83   234.2   970.3   246.5  973.38
   261.6  978.54   283.4   984.4   299.8  987.86   316.2  989.99   324.6  992.27
#Mann= 3 ,-1,0
       0      .1       0   90.03    .045       0  115.82      .1       0
Bank Sta=90.03,115.82
XS Rating Curve= 0 ,0
Exp/Cntr(USF)=0,0
Exp/Cntr=0.3,0.1

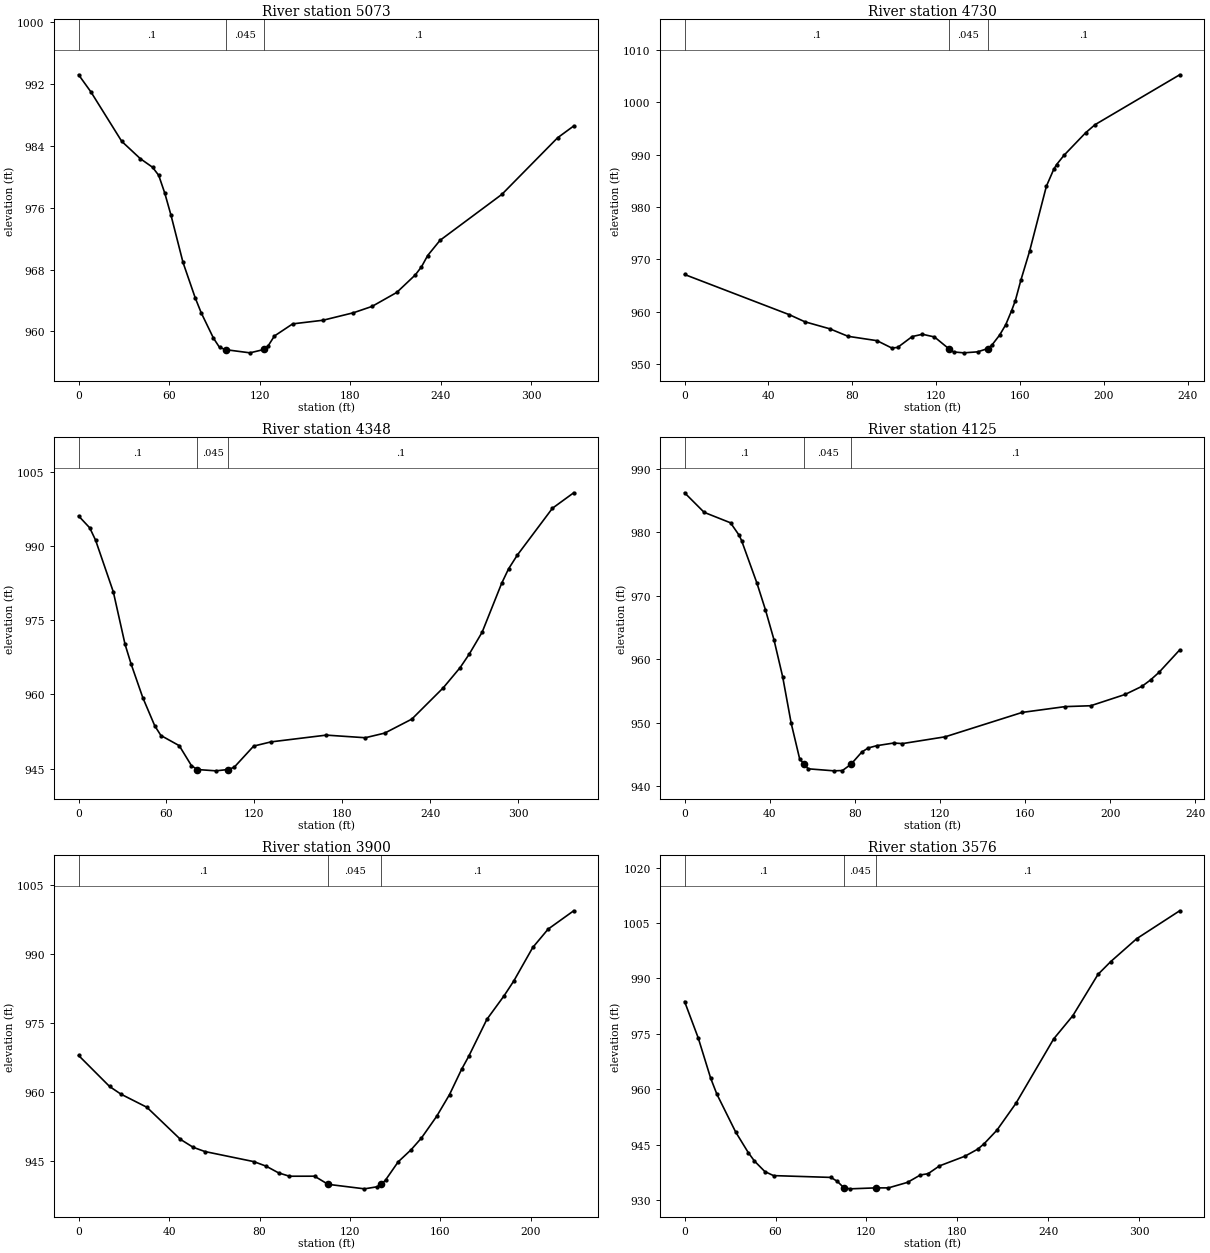
Type RM Length L Ch R = 1 ,5073    ,334.1,343,354.3
XS GIS Cut Line= 4
1614116.87284995432864.4631694261614106.33179063432917.168466018
1614123.19748554433046.8234956361614091.57430758433187.019584573
#Sta/Elev= 30
       0  993.22     8.2  990.99    28.6   984.6    40.9  982.36      49  981.25
    53.1   980.2    57.1  977.91    61.2  975.07    69.2  968.93    77.3  964.34
    81.3  962.39    89.4  959.12    93.4  957.93    97.5  957.63   113.6  957.22
  122.95957.6602   125.7  958.14   129.8   959.4   141.9  960.97     162  961.44
   182.2  962.41   194.5  963.23   210.9  965.04   223.2  967.31   227.3  968.36
   231.4  969.82   239.6  971.79   280.6  977.74   317.5  985.06   328.2  986.59
#Mann= 3 ,-1,0
       0      .1       0    97.5    .045       0  122.95      .1       0
Bank Sta=97.5,122.95
XS Rating Curve= 0 ,0
Exp/Cntr(USF)=0,0
Exp/Cntr=0.3,0.1

Type RM Length L Ch R = 1 ,4730    ,387.1,382.1,373.6
XS GIS Cut Line= 4
1613913.91508195432889.3512632831613878.81335442432911.171256072
1613759.85243861432996.3989402191613756.93550022433044.814209396
#Sta/Elev= 30
       0  967.13      50  959.46    57.4  958.11    69.3  956.77      78  955.34
    91.8  954.51    98.8  953.12   101.6  953.21   108.6   955.3   113.5  955.73
   119.2  955.22   126.1  952.96   128.3  952.36   133.2  952.19   139.8  952.38
   144.6     953   146.7  953.71   150.3  955.58   153.2  957.54     156  960.22
   157.8  962.15   160.4     966   164.6  971.57   172.6  983.95   176.1  987.17
   177.5   988.1     181  989.85   191.3  994.14   195.8  995.69   236.2 1005.21
#Mann= 3 ,-1,0
       0      .1       0   126.1    .045       0   144.6      .1       0
Bank Sta=126.1,144.6
XS Rating Curve= 0 ,0
Exp/Cntr(USF)=0,0
Exp/Cntr=0.3,0.1

Type RM Length L Ch R = 1 ,4348    ,225.4,223.4,221.3
XS GIS Cut Line= 4
1613602.00492589432672.955753921 1613597.2614492432720.390520854
1613564.05711234432832.3365708171613489.11018059432988.871301697
#Sta/Elev= 30
       0  996.04     7.6  993.64    11.6  991.14    23.7   980.7    31.7  970.11
    35.8  966.16    43.8  959.34      52  953.62    56.2  951.67    68.7  949.62
      77   945.6    80.9   944.8    93.7  944.53   102.1   944.8   106.2  945.25
   119.5  949.53   131.3  950.38   169.1  951.75   195.7  951.22     209  952.16
   227.5  954.99   248.9   961.3   260.5  965.41   266.7  968.13   275.5  972.56
   288.8  982.42   293.5  985.34   299.5  988.13   323.5  997.61     338 1000.73
#Mann= 3 ,-1,0
       0      .1       0    80.9    .045       0   102.1      .1       0
Bank Sta=80.9,102.1
XS Rating Curve= 0 ,0
Exp/Cntr(USF)=0,0
Exp/Cntr=0.3,0.1

Type RM Length L Ch R = 1 ,4125    ,219.9,225,234.8
XS GIS Cut Line= 4
1613382.60660838432635.5867852341613374.06835034432669.739817427
1613361.73531093432789.2754300991613353.19705289432866.119752532
#Sta/Elev= 30
       0  986.23     9.2  983.15    21.6   981.5    25.7  979.51    26.8  978.69
      34  972.01      38  967.81      42  963.11    46.1  957.26    50.1  949.95
    54.1  944.31    56.2943.5041    58.1  942.77    70.2  942.45    74.2   942.5
    78.2  943.48    83.3  945.41    86.3  946.05    90.3  946.41    98.3  946.83
   102.4  946.74   122.5  947.81   158.7  951.65   178.8  952.56   190.9   952.7
     207  954.47     215  955.76     219  956.76     223  957.96   232.7  961.49
#Mann= 3 ,-1,0
       0      .1       0    56.2    .045       0    78.2      .1       0
Bank Sta=56.2,78.2
XS Rating Curve= 0 ,0
Exp/Cntr(USF)=0,0
Exp/Cntr=0.3,0.1

Type RM Length L Ch R = 1 ,3900    ,327.3,323.7,318.5
XS GIS Cut Line= 4
1613231.79853654432576.9543856581613197.43468316432620.067318271
 1613114.8981887432709.7717330721613089.17800396432742.765248738
#Sta/Elev= 30
       0  967.99    13.7  961.25    18.7  959.59    30.2  956.73      45  949.77
    50.6  948.05    55.8  947.12    77.5  944.92    82.9  943.94    88.4  942.48
    93.2  941.75   104.3  941.76   110.3  939.99   126.4  939.01   131.9  939.45
   133.9  940.01   135.7  940.92   141.3  944.88     147   947.5   151.6  950.07
   158.3  954.76     164   959.5   169.3  964.95   172.5  967.82   180.5  975.83
   188.1  980.95   192.4  984.17   200.8  991.46   207.6  995.45   218.9  999.43
#Mann= 3 ,-1,0
       0      .1       0   110.3    .045       0   133.9      .1       0
Bank Sta=110.3,133.9
XS Rating Curve= 0 ,0
Exp/Cntr(USF)=0,0
Exp/Cntr=0.3,0.1

Type RM Length L Ch R = 1 ,3576    ,341.7,348.2,350.7
XS GIS Cut Line= 4
1612967.99801293432323.8393144141612956.43032095432370.110082342
1612907.26763002432519.0441166091612872.56455408432636.166997926
#Sta/Elev= 30
       0  983.77       9  973.92    17.2  963.04    21.3  958.71    33.7  948.47
      42  942.91    46.1  940.61      53  937.75    58.7  936.67    96.6  936.18
   100.8  935.11     105  933.42   109.2  933.09   126.1  933.35   134.5  933.35
   147.1  934.84   155.6  936.84   160.7  937.19   168.2   939.3     185  941.92
   193.5  943.84   197.7  945.31   206.1  948.96   218.6   956.2   243.6  973.68
   256.2  979.94   272.8  991.11   281.2  994.57   298.4 1000.79   326.7 1008.32
#Mann= 3 ,-1,0
       0      .1       0     105    .045       0   126.1      .1       0
Bank Sta=105,126.1
XS Rating Curve= 0 ,0
Exp/Cntr(USF)=0,0
Exp/Cntr=0.3,0.1

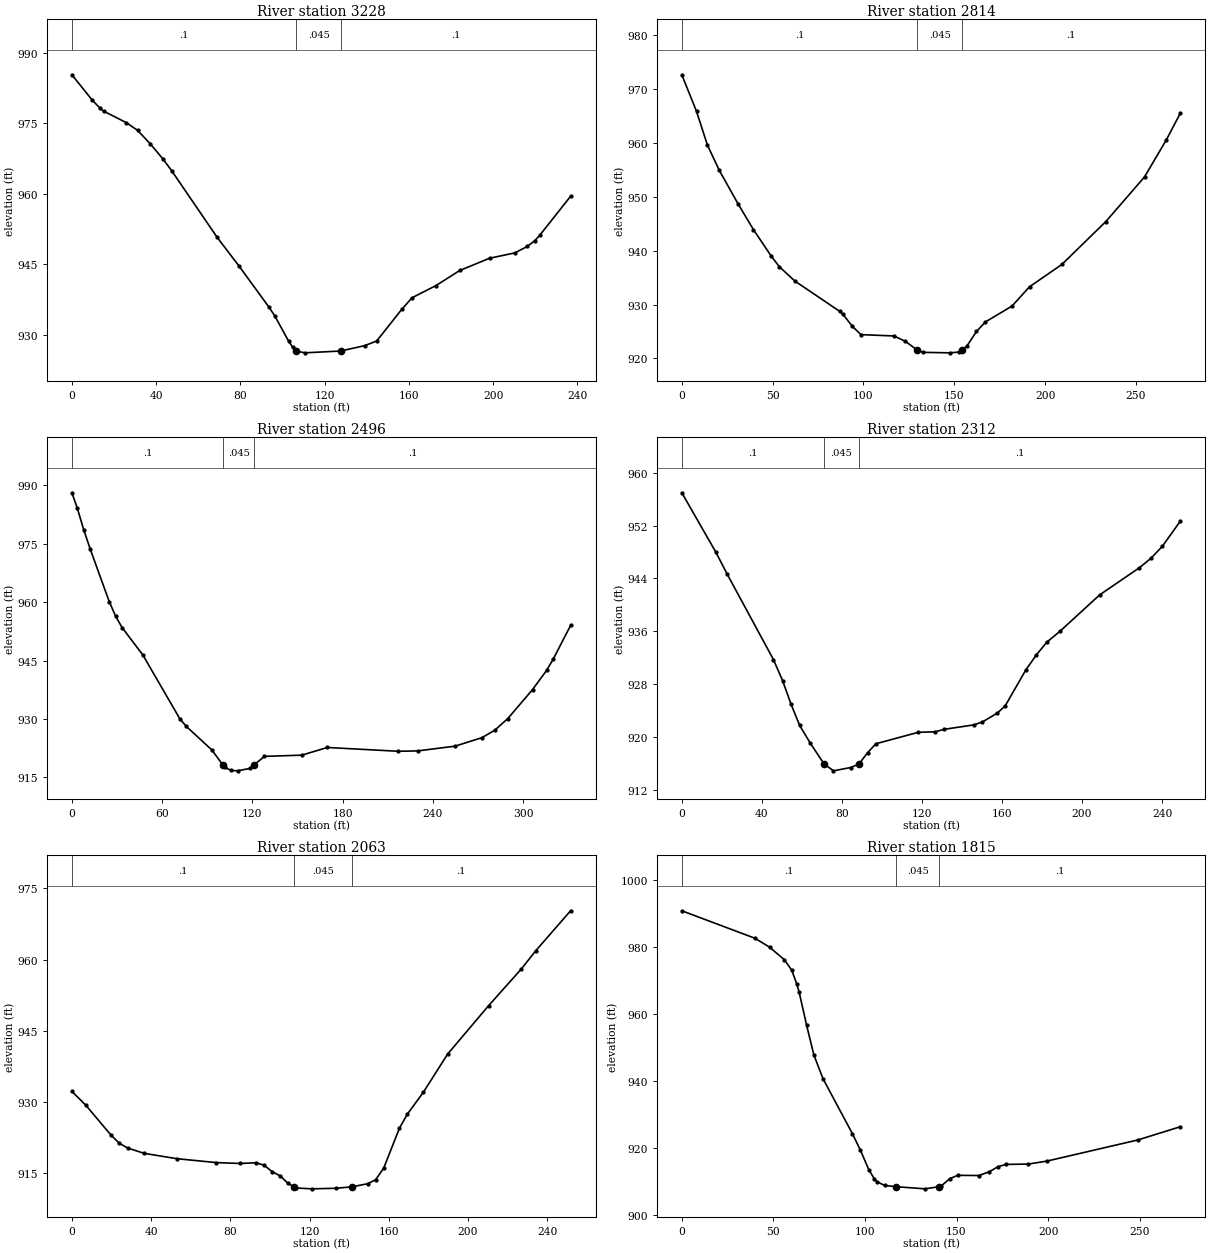
Type RM Length L Ch R = 1 ,3228    ,414.2,413.3,411.7
XS GIS Cut Line= 2
1612729.11109075432189.377677591 1612570.3445183432365.061999567
#Sta/Elev= 30
       0  985.32     9.6  979.95    13.4  978.19      15  977.59    25.8  975.14
    31.2  973.48    37.3  970.57    43.2  967.41    47.4  964.87      69  950.68
    79.4  944.57    93.6  935.82    96.4  933.93   102.9   928.6   104.9  927.27
  106.63926.5011   110.6  926.11   127.6   926.5     139  927.64   144.7  928.62
   156.6  935.35   161.5  937.83   172.9  940.44   184.2  943.65   198.3  946.25
   210.3  947.39   216.3  948.78   219.9  950.03   222.2  951.17   236.8  959.44
#Mann= 3 ,-1,0
       0      .1       0  106.63    .045       0   127.6      .1       0
Bank Sta=106.63,127.6
XS Rating Curve= 0 ,0
Exp/Cntr(USF)=0,0
Exp/Cntr=0.3,0.1

Type RM Length L Ch R = 1 ,2814    ,319.7,318.4,314.3
XS GIS Cut Line= 4
1612412.89977049431913.936383976 1612375.9474211431960.528476681
1612295.61622678432074.5987726141612265.09037294432143.683599729
#Sta/Elev= 30
       0  972.64     8.1  965.84    14.1  959.59    20.6  954.92    30.9  948.72
    39.4  943.92    49.3  938.95    53.7  937.02    62.2  934.37      87  928.72
    88.8  928.16    93.9  925.95    98.6  924.42   116.8  924.17   123.1  923.17
  129.72921.5118   132.9  921.13   147.5  921.04   152.4  921.18   154.1   921.5
     157  922.34   162.2     925   167.1  926.77   181.8  929.73   191.4   933.3
   209.2  937.44   233.4   945.4   254.7  953.68   266.7  960.55   274.5  965.56
#Mann= 3 ,-1,0
       0      .1       0  129.72    .045       0   154.1      .1       0
Bank Sta=129.72,154.1
XS Rating Curve= 0 ,0
Exp/Cntr(USF)=0,0
Exp/Cntr=0.3,0.1

Type RM Length L Ch R = 1 ,2496    ,184.1,183.6,183.4
XS GIS Cut Line= 4
1612112.46110373431745.2408759061612046.58952439431923.576127295
  1612009.637175432019.9735604771611995.17756003432055.319285978
#Sta/Elev= 30
       0  988.11     3.5  984.26     7.8  978.67    12.2  973.61    24.8  960.16
    29.1  956.36    33.4  953.46    47.2  946.41    71.7  930.07      76   928.1
    93.1  922.01   100.3918.2082   101.6  917.57   105.9  916.77   110.1  916.67
   118.1  917.28   121.2  918.23     128  920.39   152.8   920.7   169.8  922.67
   216.8   921.7   229.9  921.79   254.7  923.01   272.5  925.18   281.1  927.11
   289.7  930.07   306.2  937.54   315.6   942.5   319.9  945.33   331.5  954.02
#Mann= 3 ,-1,0
       0      .1       0   100.3    .045       0   121.2      .1       0
Bank Sta=100.3,121.2
XS Rating Curve= 0 ,0
Exp/Cntr(USF)=0,0
Exp/Cntr=0.3,0.1

Type RM Length L Ch R = 1 ,2312    ,235.9,249,269.4
XS GIS Cut Line= 4
1611940.84493195431740.7525043091611906.87929637431773.546911078
1611872.91366079431870.7589025711611796.78378793431934.005258482
#Sta/Elev= 30
       0  956.95      17  947.97    22.7  944.63    45.8  931.71    50.4  928.51
    54.6  924.96    58.9  921.75    64.3  919.03   71.04915.9508    75.8  914.89
    84.3  915.39    88.5  915.91    92.8  917.62      97  918.99   118.2  920.72
   126.6  920.79   130.9  921.16   145.9  921.84   150.2  922.28   157.7  923.63
   161.6  924.72     172   930.2   177.2  932.43   182.4  934.35   188.9  935.98
   208.8   941.5   228.7  945.62   234.4  947.03   240.1  948.84   249.2  952.69
#Mann= 3 ,-1,0
       0      .1       0   71.04    .045       0    88.5      .1       0
Bank Sta=71.04,88.5
XS Rating Curve= 0 ,0
Exp/Cntr(USF)=0,0
Exp/Cntr=0.3,0.1

Type RM Length L Ch R = 1 ,2063    ,254.6,248.4,242.7
XS GIS Cut Line= 4
1611866.84589222431644.0622317911611826.05199266431657.343966532
1611686.59377788431644.0622317911611620.18510417431662.087443225
#Sta/Elev= 30
       0  932.28     7.1  929.33    19.7  923.09    23.9  921.37    28.1  920.36
    36.5  919.23      53  918.11      73  917.28      85   917.1    93.1  917.25
    97.1  916.72   101.1  915.37   105.1  914.51   109.1  912.92  112.27912.1623
   113.2  911.94   121.2  911.76   133.2  911.88   141.3  912.18   149.3  912.83
   153.3  913.66   157.4  916.08   165.4  924.54   169.4   927.5   177.4  932.06
   189.7  940.12   210.4  950.32     227  958.08   234.3  961.93   251.8   970.3
#Mann= 3 ,-1,0
       0      .1       0  112.27    .045       0   141.3      .1       0
Bank Sta=112.27,141.3
XS Rating Curve= 0 ,0
Exp/Cntr(USF)=0,0
Exp/Cntr=0.3,0.1

Type RM Length L Ch R = 1 ,1815    ,240.6,238.7,235.4
XS GIS Cut Line= 4
1611883.72517917431378.7470944541611801.18868471431388.234047841
1611694.93480678 431438.514900791611631.37221909431471.719237644
#Sta/Elev= 30
       0  990.73    39.9  982.54    47.9  979.89      56  976.11      60  973.04
    62.7  968.99      64  966.62    68.1  956.68    72.1  947.73    77.1  940.63
    93.1  924.28    97.5  919.33   102.1  913.48   105.1  910.77   106.4  909.92
   110.8  908.78   117.2   908.4   132.9  907.77  140.29908.4092   141.8  908.69
   146.2  910.75   150.6   911.8   162.2  911.74     168  912.89   172.8  914.43
   177.2  915.06   189.2  915.16   199.3  916.04   248.9  922.34   272.3  926.31
#Mann= 3 ,-1,0
       0      .1       0   117.2    .045       0  140.29      .1       0
Bank Sta=117.2,140.29
XS Rating Curve= 0 ,0
Exp/Cntr(USF)=0,0
Exp/Cntr=0.3,0.1