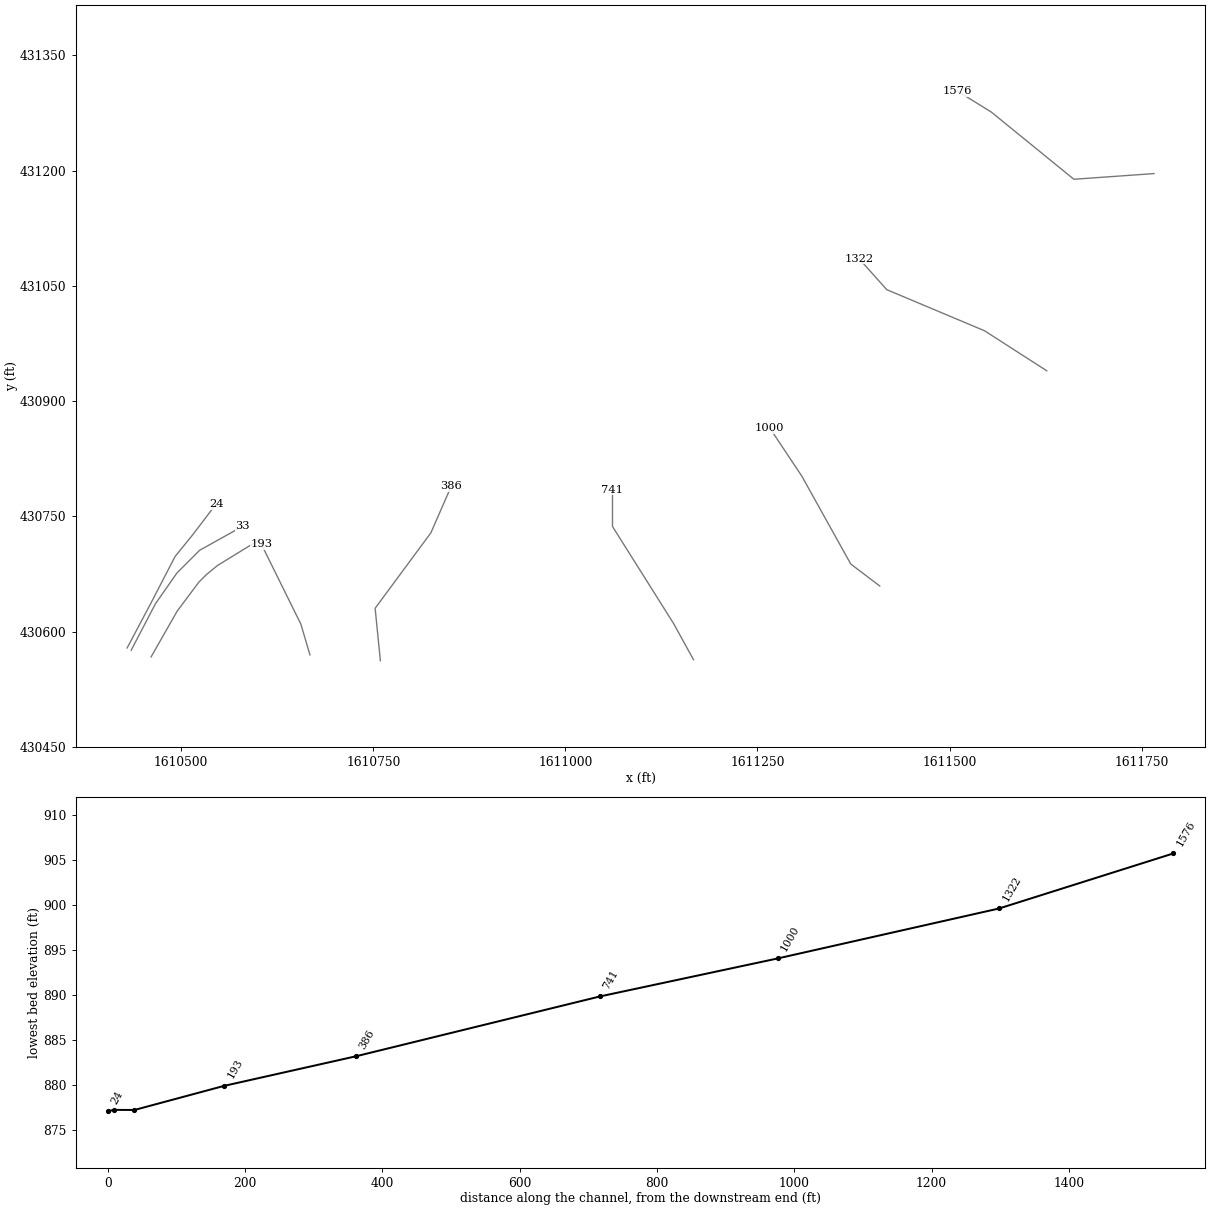
HEC-RAS study PROCTRCKT1.prj: PROCTRCKT1

--- PROCTRCKT1.g01 (geometry) --- (continued)

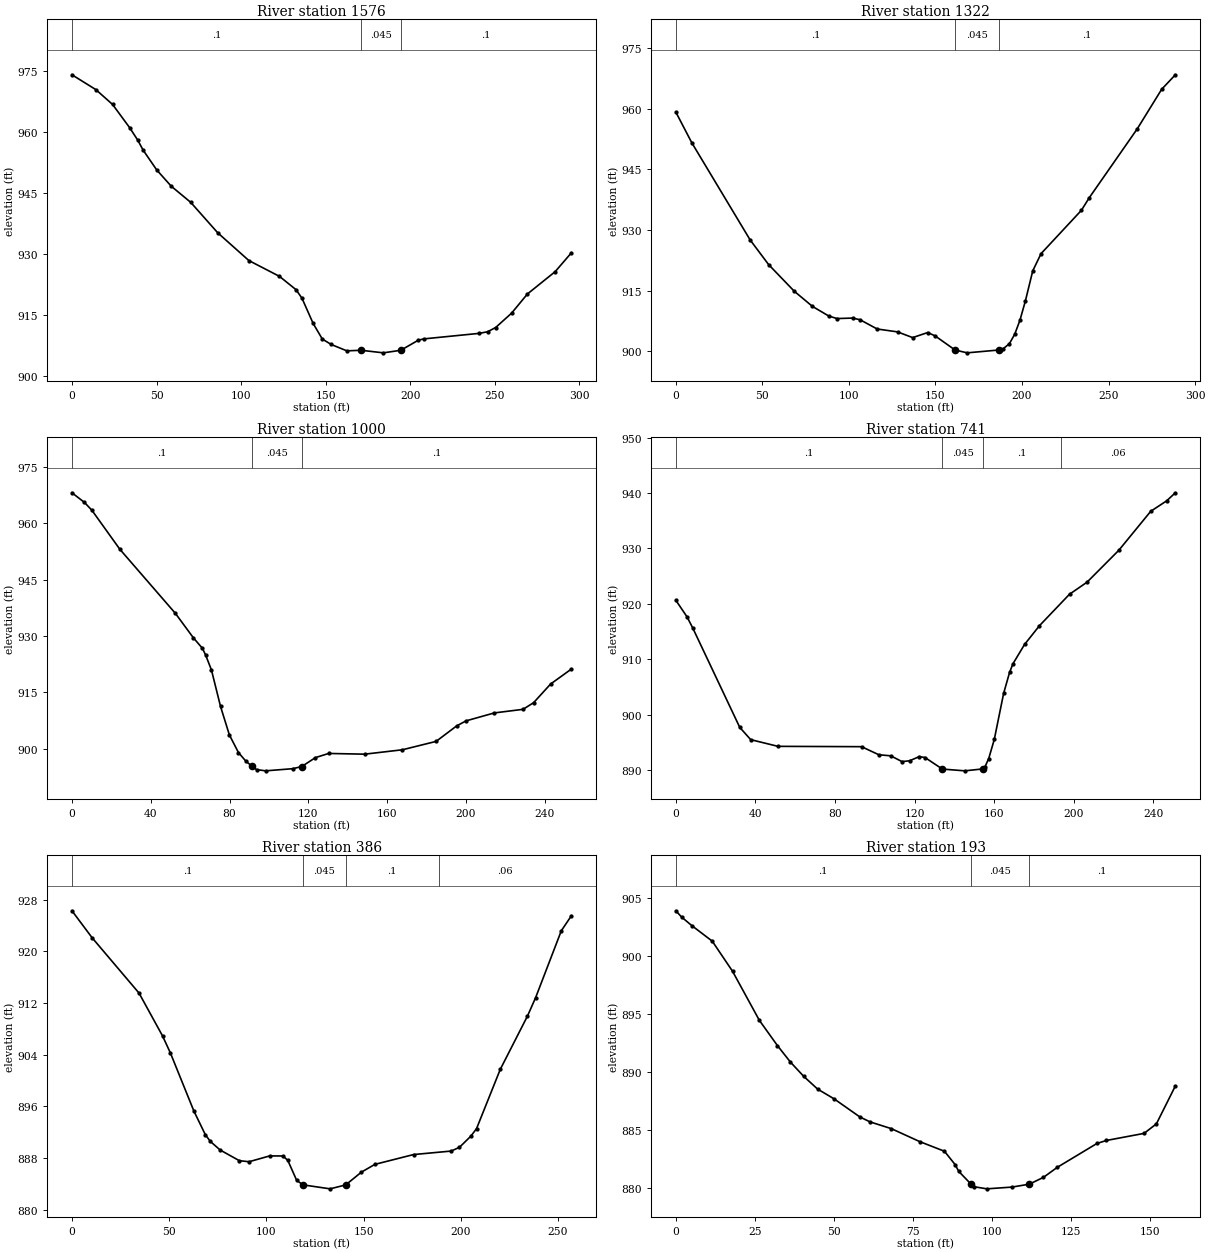
Type RM Length L Ch R = 1 ,1576    ,249.7,254,256.7
XS GIS Cut Line= 4
1611766.12961304 431196.137918271611661.77312579431188.759176747
1611554.25432074431276.249969091 1611509.9818716431303.656723319
#Sta/Elev= 30
       0  974.13    14.1  970.49      24  966.84    34.1  961.13      39  957.99
    42.1  955.59    50.1  950.74    58.7  946.73    70.2  942.77    86.2  935.27
   104.6  928.45   122.7  924.56   132.5  921.28     136  919.18   142.6  912.98
     148  909.16   153.2  907.83   162.5  906.25     171  906.39   184.1  905.76
   194.4  906.39   204.7  908.85     208  909.19   240.8  910.55   245.8  910.95
   250.5  911.99   259.9  915.51   269.3  920.24   285.7  925.73   295.3  930.37
#Mann= 3 ,-1,0
       0      .1       0     171    .045       0   194.4      .1       0
Bank Sta=171,194.4
XS Rating Curve= 0 ,0
Exp/Cntr(USF)=0,0
Exp/Cntr=0.3,0.1

Type RM Length L Ch R = 1 ,1322    ,332.3,322.4,315.7
XS GIS Cut Line= 4
1611626.44760804430939.5433211721611545.47376417430991.597935091
1611418.22915237431045.0985105071611382.08011493431085.585432444
#Sta/Elev= 30
       0  959.17     9.2   951.6    42.9  927.57    53.6  921.46    68.4  914.88
    78.9  911.13    88.4  908.73    93.1  908.12   102.1  908.24   106.4  907.83
   116.3  905.54   128.1  904.82   136.8  903.41   145.5  904.66   149.8  903.83
   161.3900.3405   168.3  899.64   186.6  900.34   188.9  900.57   192.7   901.9
   195.8  904.26   198.8  907.71   201.9  912.41   206.2  919.93     211  924.18
   234.3  934.89   238.9  938.04   266.6  955.06   280.7  964.84   288.6  968.42
#Mann= 3 ,-1,0
       0      .1       0   161.3    .045       0   186.6      .1       0
Bank Sta=161.3,186.6
XS Rating Curve= 0 ,0
Exp/Cntr(USF)=0,0
Exp/Cntr=0.3,0.1

Type RM Length L Ch R = 1 ,1000    ,262.4,258.8,261.4
XS GIS Cut Line= 4
1611409.12111561430659.4428182871611371.38152052430688.072855942
1611307.61461847430802.5930065631611265.97092733430865.058543266
#Sta/Elev= 30
       0  968.15     6.3   965.6    10.1  963.51    24.3  953.11    52.5  936.03
    61.6  929.54    66.2  926.73    67.8  924.99    70.8  920.95    75.4  911.25
    79.9  903.65    84.5  898.96    88.3  896.64    91.3  895.36    93.7  894.42
    98.3  894.09     112  894.66   116.6  895.23   123.6  897.62   130.3  898.72
   148.6  898.53   167.7   899.7   184.8  901.93   195.2  906.04     200   907.4
   214.4  909.52   228.9  910.47   234.3  912.24   242.9   917.2   253.5  921.21
#Mann= 3 ,-1,0
       0      .1       0    91.3    .045       0   116.6      .1       0
Bank Sta=91.3,116.6
XS Rating Curve= 0 ,0
Exp/Cntr(USF)=0,0
Exp/Cntr=0.3,0.1

Type RM Length L Ch R = 1 ,741     ,367.5,355.4,343.4
XS GIS Cut Line= 4
1611166.73173352430563.5543278481611140.96469963430610.403480375
1611061.32114033430736.8961921981611061.32114033430784.916573538
#Sta/Elev= 30
       0  920.64     5.6  917.66     8.5  915.63    32.1  897.71    37.6   895.5
    51.3  894.29    93.3  894.23     102  892.77     108  892.58   113.6  891.54
   117.4  891.68   122.3  892.44   125.2  892.27   133.9  890.19   145.2  889.87
   154.3  890.22   155.3  890.57   157.2  892.08     160  895.53   164.7  903.85
   167.7  907.65   169.4   909.2   175.2  912.67   182.7  916.06   197.8  921.74
   206.6  923.91   222.6  929.68   238.6   936.7   246.6  938.59     251  940.05
#Mann= 4 ,-1,0
       0      .1       0   133.9    .045       0   154.3      .1       0
  193.47     .06       0
Bank Sta=133.9,154.3
XS Rating Curve= 0 ,0
Exp/Cntr(USF)=0,0
Exp/Cntr=0.3,0.1

Type RM Length L Ch R = 1 ,386     ,176.3,192.7,199.3
XS GIS Cut Line= 4
1610759.27124927430562.1704115451610752.44064284430630.476475928
1610825.01583624 430728.666443481610851.48443619430789.288075621
#Sta/Elev= 30
       0  926.29    10.4   922.1    34.5  913.54    46.6   906.9    50.6  904.29
    62.7  895.28    68.6  891.61    71.2  890.56    76.2  889.24    86.1  887.58
    91.1  887.42   101.7  888.32   108.5  888.31     111  887.64   115.6  884.52
  118.88883.8341   132.8  883.22   140.8  883.83   148.9  885.81   155.8  887.01
   175.7  888.53     195  889.07   199.3  889.65   205.2  891.39   208.1  892.55
   220.3  901.73   234.3  909.99   238.5  912.85   251.7   923.2   256.9  925.53
#Mann= 4 ,-1,0
       0      .1       0  118.88    .045       0   140.8      .1       0
  188.65     .06       0
Bank Sta=118.88,140.8
XS Rating Curve= 0 ,0
Exp/Cntr(USF)=0,0
Exp/Cntr=0.3,0.1

Type RM Length L Ch R = 1 ,193     ,137.3,130.1,119.5
XS GIS Cut Line= 3
1610667.61833292430569.7805588211610655.77524809430609.802017907
1610604.31908641430713.939487979
#Sta/Elev= 30
       0  903.89     1.8  903.35       5  902.62    11.5  901.27    17.9  898.68
    26.4  894.44    32.1  892.27    36.2  890.85    40.4  889.62    44.8  888.52
      50  887.68    58.2  886.11    61.4  885.69    68.1  885.11    77.1  883.99
    84.9  883.16    88.3     882    89.4  881.43    93.2880.3538    94.3   880.1
    98.3  879.92   106.2  880.07   111.7  880.32   116.2  880.91   120.6  881.78
   133.1  883.83   136.1  884.09     148   884.7   151.9  885.52   157.9  888.79
#Mann= 3 ,-1,0
       0      .1       0    93.2    .045       0   111.7      .1       0
Bank Sta=93.2,111.7
XS Rating Curve= 0 ,0
Exp/Cntr(USF)=0,0
Exp/Cntr=0.3,0.1

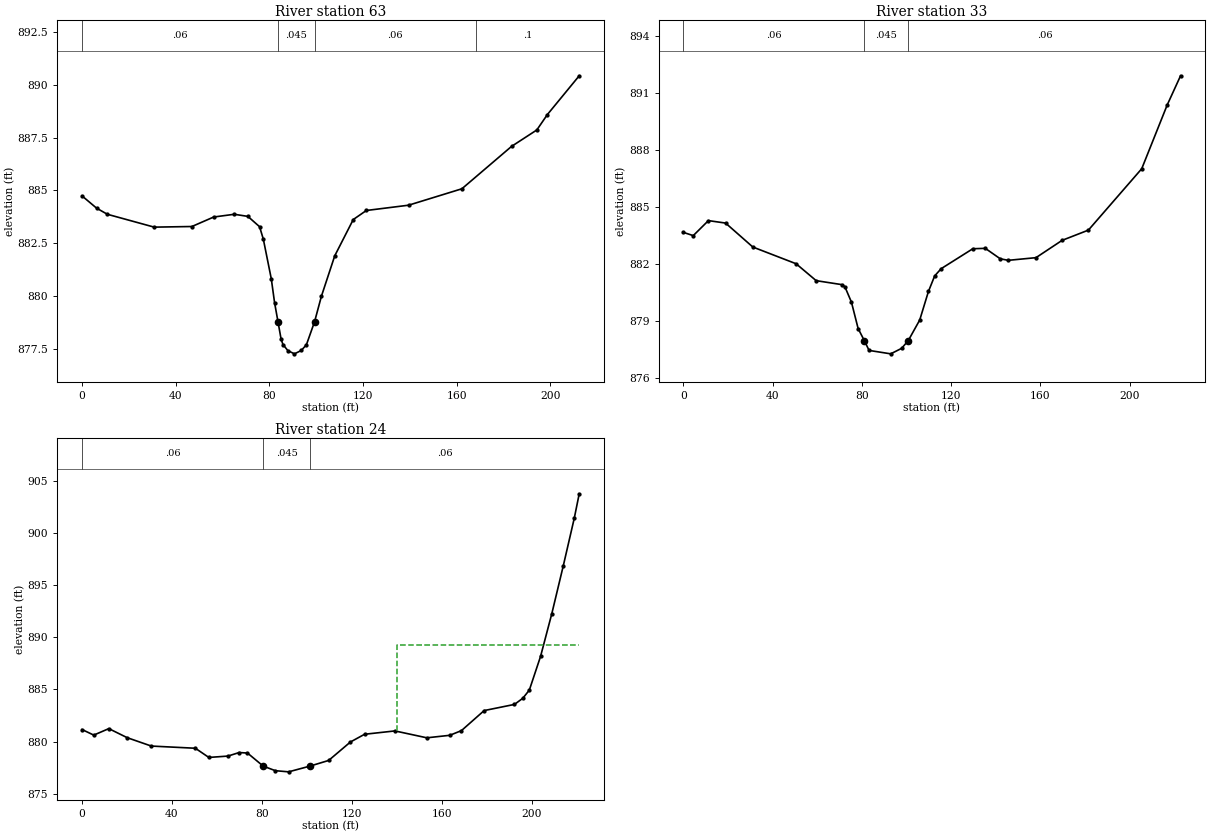
Type RM Length L Ch R = 1 ,63      ,31.1,29.9,30.4
XS GIS Cut Line= 6
1610460.89547783430567.1734318651610494.78894438430626.701996164
1610522.95223485 430664.35509104 1610533.0542847430674.457140885
1610547.15764356430686.0232637231610601.86092162430719.641149639
#Sta/Elev= 30
       0  884.74     6.2  884.16    10.8  883.87    30.8  883.26    46.9  883.29
    56.2  883.74      65  883.87    70.8  883.77    75.8  883.28    77.4  882.69
    80.8  880.81    82.2  879.68   83.71878.7422      85  877.94    85.8  877.69
    87.9   877.4    90.7  877.25    93.6  877.41    95.8  877.68    99.3  878.78
   102.2  879.98   107.9   881.9   115.8  883.62   121.4  884.05   139.4   884.3
   162.2  885.08   183.4  887.09   194.2  887.87   198.7   888.6   212.3  890.44
#Mann= 4 ,-1,0
       0     .06       0   83.71    .045       0    99.3     .06       0
  168.05      .1       0
Bank Sta=83.71,99.3
XS Rating Curve= 0 ,0
Exp/Cntr(USF)=0,0
Exp/Cntr=0.3,0.1

Type RM Length L Ch R = 1 ,33      ,7.3,9,9.9
XS GIS Cut Line= 5
1610434.92746241430575.806123454 1610466.6256539430636.497923286
1610494.48282165 430676.293877221610524.04314533430705.917370856
1610579.91906761430737.009477299
#Sta/Elev= 30
       0  883.65     4.4  883.48    11.2  884.27    18.9  884.14    31.1  882.88
    50.5     882    59.5  881.11    71.1   880.9    72.4  880.78    75.3  879.98
    78.3  878.59    81.1  877.95    83.2  877.44    92.9  877.26    97.8  877.55
  100.77877.9575   105.9  879.04   109.8  880.54   112.6  881.36   115.5  881.74
   129.7  882.79   135.3  882.81     142  882.26   145.6  882.18     158  882.32
   169.7  883.23   181.5  883.77   205.4     887   216.8  890.35   222.8  891.89
#Mann= 3 ,-1,0
       0     .06       0    81.1    .045       0  100.77     .06       0
Bank Sta=81.1,100.77
XS Rating Curve= 0 ,0
Exp/Cntr(USF)=0,0
Exp/Cntr=0.3,0.1

Type RM Length L Ch R = 1 ,24      ,,,
XS GIS Cut Line= 5
1610429.69768585  430578.81701321610461.11544489430638.028536899
1610492.03383987  430697.72246781610515.18242026430726.267697452
1610545.56562787430766.229522615
#Sta/Elev= 30
       0  881.16     5.2  880.63    11.9  881.25    20.1  880.38    30.8  879.58
    50.4  879.37    56.4  878.49    64.9  878.62    69.9  878.96    73.6  878.91
   80.58877.6604      86  877.22    91.9  877.11   101.4  877.66   109.7   878.2
   119.4  879.97   125.7  880.71   139.2  881.03   153.4  880.37   163.6  880.61
   168.8  881.06   178.9  882.98   192.4  883.57   196.1  884.16     199  884.94
     204  888.17     209  892.26   214.1  896.84     219  901.41   221.2  903.75
#Mann= 3 ,-1,0
       0     .06       0   80.58    .045       0   101.4     .06       0
#XS Ineff= 2 , 0
                          140.26          889.26
Permanent Ineff=
       F       F
Bank Sta=80.58,101.4
XS Rating Curve= 0 ,0
Exp/Cntr(USF)=0,0
Exp/Cntr=0.3,0.1
LCMann Table=0

Chan Stop Cuts=-1
Use User Specified Reach Order=0
Composite Channel Slope=5